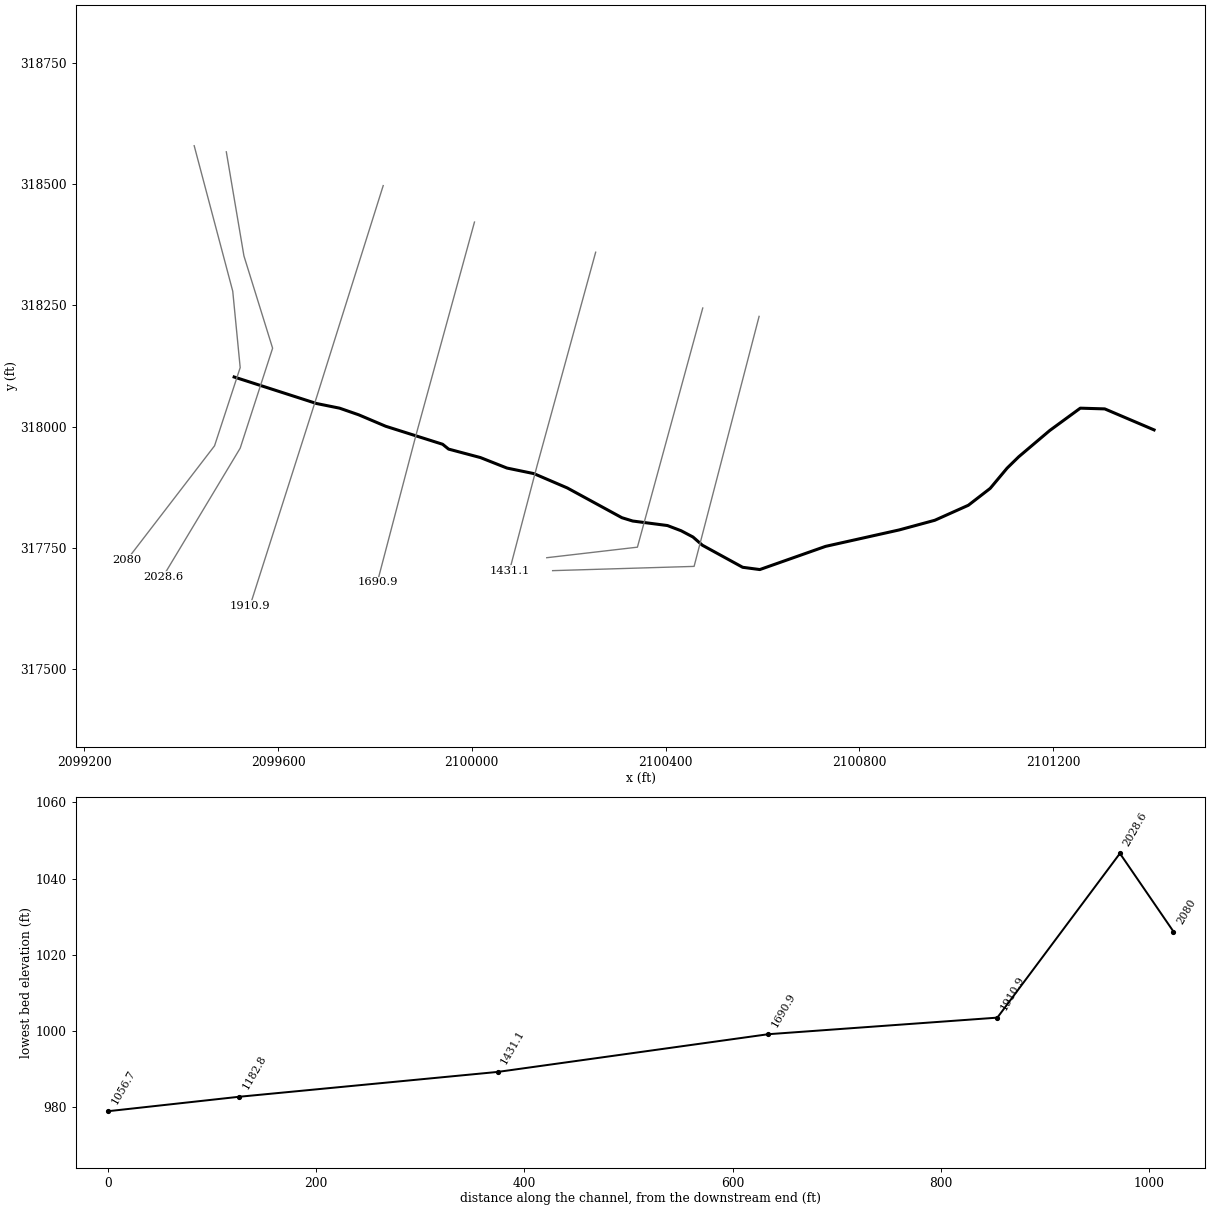
--- NP70.prj (project) ---

Proj Title=NP70
Current Plan=p01
Default Exp/Contr=0,0
English Units
Geom File=g01
Flow File=f01
Plan File=p01
BEGIN DESCRIPTION:
END DESCRIPTION:
DSS Export Rating Curves= 0
DSS Export Rating Curve Sorted= 0
DSS Export Volume Flow Curves= 0
DXF OffsetX= 0
DXF OffsetY= 0
DXF ScaleX= 0
DXF ScaleY= 0

--- NP70.p01 (plan) ---

Plan Title=Floodplain
Program Version=4.00
Geom File=g01
Flow File=f01
K Sum by GR=0
Std Step Tol=0.01
Critical Tol=0.01
Num of Std Step Trials=20
Max Error Tol=0.3
Flow Tol Ratio=0.001
Split Flow NTrial=30
Split Flow Tol=0.02
Split Flow Ratio=0.02
Log Output Level=0
Friction Slope Method=1
Unsteady Friction Slope Method=2
Unsteady Bridges Friction Slope Method=1
Global Log Level=0
CheckData=False
Run HTab=0
Run UNet=0
Run PostProcess=0
UNET Theta=0
UNET Theta Warmup=0
UNET ZTol=0
UNET ZSATol=0
UNET MxIter=0
UNET MaxInSteps=0
UNET DtIC=0
UNET DtMin=0
UNET MaxCRTS=0
UNET WFStab=0
UNET SFStab=0
UNET WFX=0
UNET SFX=0
UNET DSS MLevel=0
UNET DZMax Abort=0
UNET Convert EG Bridges=0
UNET Use Existing IB Tables=0
UNET Froude Limit=0
UNET Froude Power=0
Write IC File=0
Echo Input=False
Echo Output=False
Write Detailed=0

--- NP70.f01 (steady flow) ---

Flow Title=NFF Regression Equation
Program Version=4.00
Number of Profiles=1
Profile Names=P100yr
River Rch & RM=NP70,Main      ,2080
     117
River Rch & RM=NP70,Main      ,1182.8
     124
Boundary for River Rch & Prof#=NP70,Main      ,1
Up Type=0
Dn Type=3
Dn Slope=0.031456

--- NP70.g01 (geometry) ---

Geom Title=USGS 10m DEM
Program Version=4.00

River Reach=NP70            ,Main
Reach XY= 30
     2099509.272      318102.303     2099679.453      318047.556
     2099726.989      318037.971     2099766.537      318024.254
     2099822.296      318000.607     2099939.783       317963.48
     2099952.014       317953.53     2100017.789      317936.041
     2100072.544      317914.404     2100128.194      317902.908
      2100197.16      317873.347     2100309.845      317811.956
     2100332.108       317805.11     2100403.908      317795.775
     2100432.257      317784.992     2100456.636      317772.113
     2100476.012      317755.179     2100559.232      317709.633
     2100594.612      317704.933     2100730.378      317752.777
     2100882.472      317786.725     2100955.967      317806.647
     2101025.282       317837.66     2101070.313      317872.455
     2101105.212      317914.219     2101129.212      317937.669
     2101193.239      317991.857     2101256.361      318037.982
     2101306.841      318036.475      2101408.66      317993.139

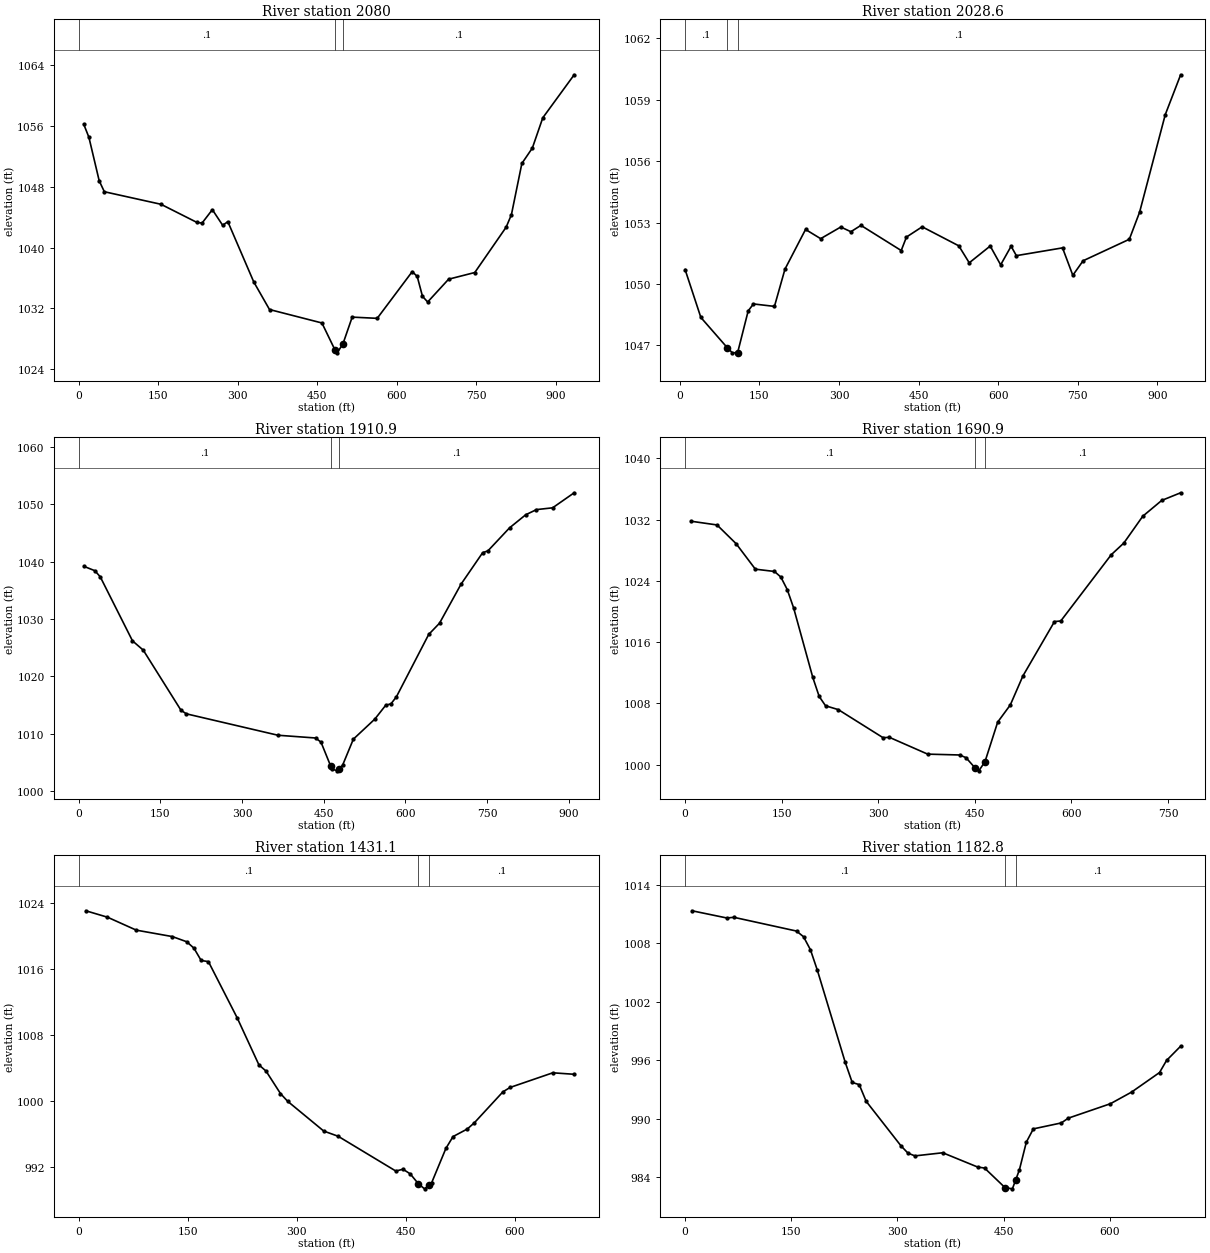
Type RM Length L Ch R = 1 ,2080    ,51.4,51.4,51.5
XS GIS Cut Line= 5
     2099426.805      318579.496      2099506.42      318279.305
     2099521.785      318121.698     2099468.848      317960.275
     2099288.372        317725.5
#Sta/Elev= 30
     9.7 1056.21    19.4  1054.5    38.8 1048.78    48.5 1047.34   155.3 1045.69
   223.2  1043.3   232.9 1043.22   252.3 1044.98   271.7 1042.93   281.5  1043.4
   330.4 1035.47   360.1 1031.84     459 1030.07   483.7 1026.51   487.8 1026.14
   498.7 1027.33   516.1 1030.84   563.3 1030.68   629.4 1036.83   638.8 1036.19
   648.7 1033.58   658.5 1032.83     698 1035.83   747.4 1036.71   806.6 1042.68
   816.5 1044.32   836.2 1051.06     856 1053.09   875.7 1057.07   934.9 1062.73
#Mann= 3 , 0 , 0
       0      .1       0   483.7    .045       0   498.7      .1       0
Bank Sta=483.7,498.7
XS Rating Curve= 0 ,0
Exp/Cntr=0.3,0.1

Type RM Length L Ch R = 1 ,2028.6  ,117.5,117.7,117.8
XS GIS Cut Line= 5
     2099493.131      318566.915     2099529.534      318352.084
     2099588.718      318161.734     2099521.785        317955.4
     2099362.206      317689.996
#Sta/Elev= 30
     9.9  1050.7    39.6 1048.36    89.1 1046.89      99 1046.63   108.9 1046.64
   128.8 1048.68   138.7 1049.02   178.3  1048.9   198.1 1050.72   236.9 1052.66
   265.4 1052.21   303.3 1052.78   322.3 1052.55   341.3 1052.86   417.2 1051.63
   427.1 1052.29   456.7 1052.79   525.7 1051.86   545.4 1051.03   584.9 1051.85
   604.6 1050.93   624.3 1051.84   634.2 1051.38   721.2 1051.76   740.6 1050.42
     760 1051.13   847.1 1052.18   866.4  1053.5   914.8 1058.27   943.8 1060.22
#Mann= 3 , 0 , 0
     9.9      .1       0    89.1    .045       0   108.9      .1       0
Bank Sta=89.1,108.9
XS Rating Curve= 0 ,0
Exp/Cntr=0.3,0.1

Type RM Length L Ch R = 1 ,1910.9  ,219,220,221.1
XS GIS Cut Line= 3
     2099817.071      318497.214       2099680.4      318063.221
     2099541.935      317629.802
#Sta/Elev= 30
     9.9 1039.17    29.7 1038.42    39.6 1037.37    98.9  1026.2   118.7 1024.58
   187.9 1014.12   197.8 1013.49     366 1009.76   435.2 1009.28   445.1 1008.55
   462.7 1004.43   464.9 1003.91   474.8 1003.56   477.7 1003.85   484.7 1004.53
   504.5 1009.08     544 1012.58   563.8 1014.97   573.7 1015.25   583.6 1016.46
   642.9 1027.32   662.7 1029.27   702.3 1036.08   741.9 1041.55   751.7 1041.88
   791.3 1045.88     821 1048.16   840.8 1049.06   870.4 1049.37     910 1051.99
#Mann= 3 , 0 , 0
       0      .1       0   462.7    .045       0   477.7      .1       0
Bank Sta=462.7,477.7
XS Rating Curve= 0 ,0
Exp/Cntr=0.3,0.1

Type RM Length L Ch R = 1 ,1690.9  ,259.6,259.8,259.9
XS GIS Cut Line= 3
     2100005.506      318422.016     2099884.726      317982.247
     2099805.011       317679.11
#Sta/Elev= 30
     9.9 1031.78    49.6  1031.3    79.3 1028.85   109.1 1025.53   138.8 1025.23
   148.7  1024.5   158.6 1022.87   168.5 1020.48   198.3  1011.4   208.2 1008.92
   218.1  1007.7   237.9  1007.2   307.3 1003.54   317.3 1003.58   376.7 1001.39
   426.3 1001.28   436.2 1000.93   450.7  999.55   456.1  999.21   465.7 1000.41
   485.4 1005.57     505 1007.81   524.6  1011.6   573.6 1018.69   583.4 1018.77
   661.8 1027.42   681.3 1028.94   710.7 1032.44   740.1  1034.5   769.5  1035.5
#Mann= 3 , 0 , 0
       0      .1       0   450.7    .045       0   465.7      .1       0
Bank Sta=450.7,465.7
XS Rating Curve= 0 ,0
Exp/Cntr=0.3,0.1

Type RM Length L Ch R = 1 ,1431.1  ,248.6,248.4,248.1
XS GIS Cut Line= 3
     2100255.741      318359.797     2100134.961      317920.028
     2100077.617      317701.962
#Sta/Elev= 30
     9.9 1023.06    39.7 1022.28    79.3 1020.71   128.9 1019.93   148.7  1019.3
   158.6 1018.52   168.5 1017.03   178.5 1016.89   218.1 1010.06   247.9 1004.37
   257.8  1003.6   277.6 1000.88   287.5  999.94   337.1  996.33   356.9   995.7
   436.2  991.48   446.1   991.7   456.1  991.13   467.3  989.93   475.7  989.32
   482.3  989.82   485.5  990.06   505.1  994.23   514.9  995.66   534.5  996.58
   544.3  997.34   583.5 1001.09   593.3 1001.62   652.1  1003.4   681.5 1003.22
#Mann= 3 , 0 , 0
       0      .1       0   467.3    .045       0   482.3      .1       0
Bank Sta=467.3,482.3
XS Rating Curve= 0 ,0
Exp/Cntr=0.3,0.1

Type RM Length L Ch R = 1 ,1182.8  ,125,126,126.9
XS GIS Cut Line= 3
     2100476.846      318244.664     2100341.929      317751.136
      2100154.75      317729.392
#Sta/Elev= 30
     9.8 1011.32      59 1010.58    68.9 1010.65   157.4 1009.24   167.3 1008.66
   177.1 1007.32   186.9 1005.21   226.3  995.76   236.1  993.71     246  993.49
   255.8  991.78     305  987.21   314.9  986.46   324.7  986.18     364   986.5
   413.2  985.04   423.1  984.93   451.9  982.93   462.4   982.8   466.9  983.68
   472.3  984.75   482.1  987.59     492  988.95   531.5  989.56   541.4  990.05
   600.9  991.53   630.7  992.72   670.3  994.73   680.2  995.97   700.1  997.43
#Mann= 3 , 0 , 0
       0      .1       0   451.9    .045       0   466.9      .1       0
Bank Sta=451.9,466.9
XS Rating Curve= 0 ,0
Exp/Cntr=0.3,0.1

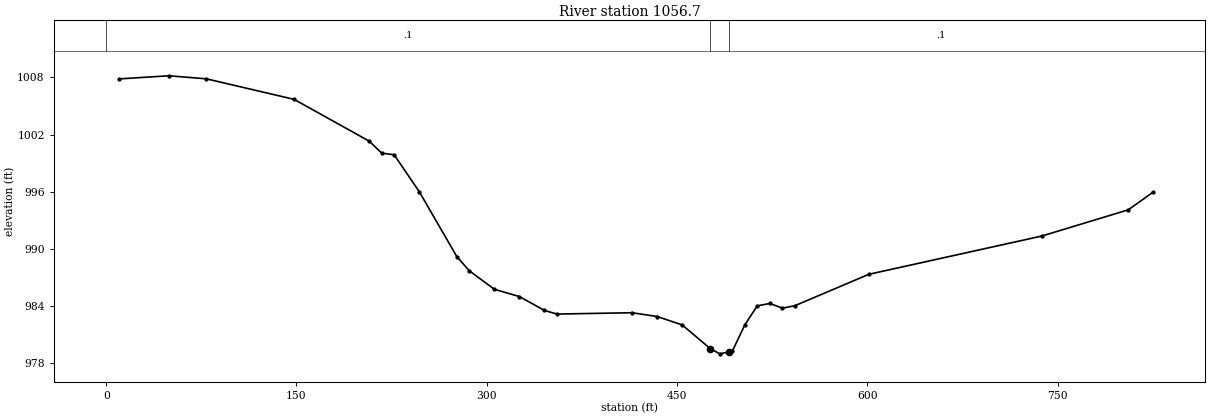
Type RM Length L Ch R = 1 ,1056.7  ,1061.2,1056.7,1052.5
XS GIS Cut Line= 3
     2100593.176       318227.37     2100458.956      317711.475
     2100166.881      317702.703
#Sta/Elev= 30
     9.9 1007.83    49.4 1008.16      79 1007.84   148.1 1005.69   207.3 1001.31
   217.2 1000.05     227  999.88   246.8  996.01   276.4  989.21   286.3  987.71
     306  985.78   325.8  985.01   345.5  983.56   355.4  983.18   414.6  983.32
   434.4  982.92   454.1  982.04   476.2  979.56   483.7  979.01   491.2  979.22
   493.6  979.29   503.5  982.06   513.3  984.04   523.2  984.29   533.1   983.8
   542.8  984.05   601.3  987.35   737.6  991.36   805.8  994.11   825.3  995.96
#Mann= 3 , 0 , 0
       0      .1       0   476.2    .045       0   491.2      .1       0
Bank Sta=476.2,491.2
XS Rating Curve= 0 ,0
Exp/Cntr=0.3,0.1

Chan Stop Cuts=-1
Use User Specified Reach Order=0